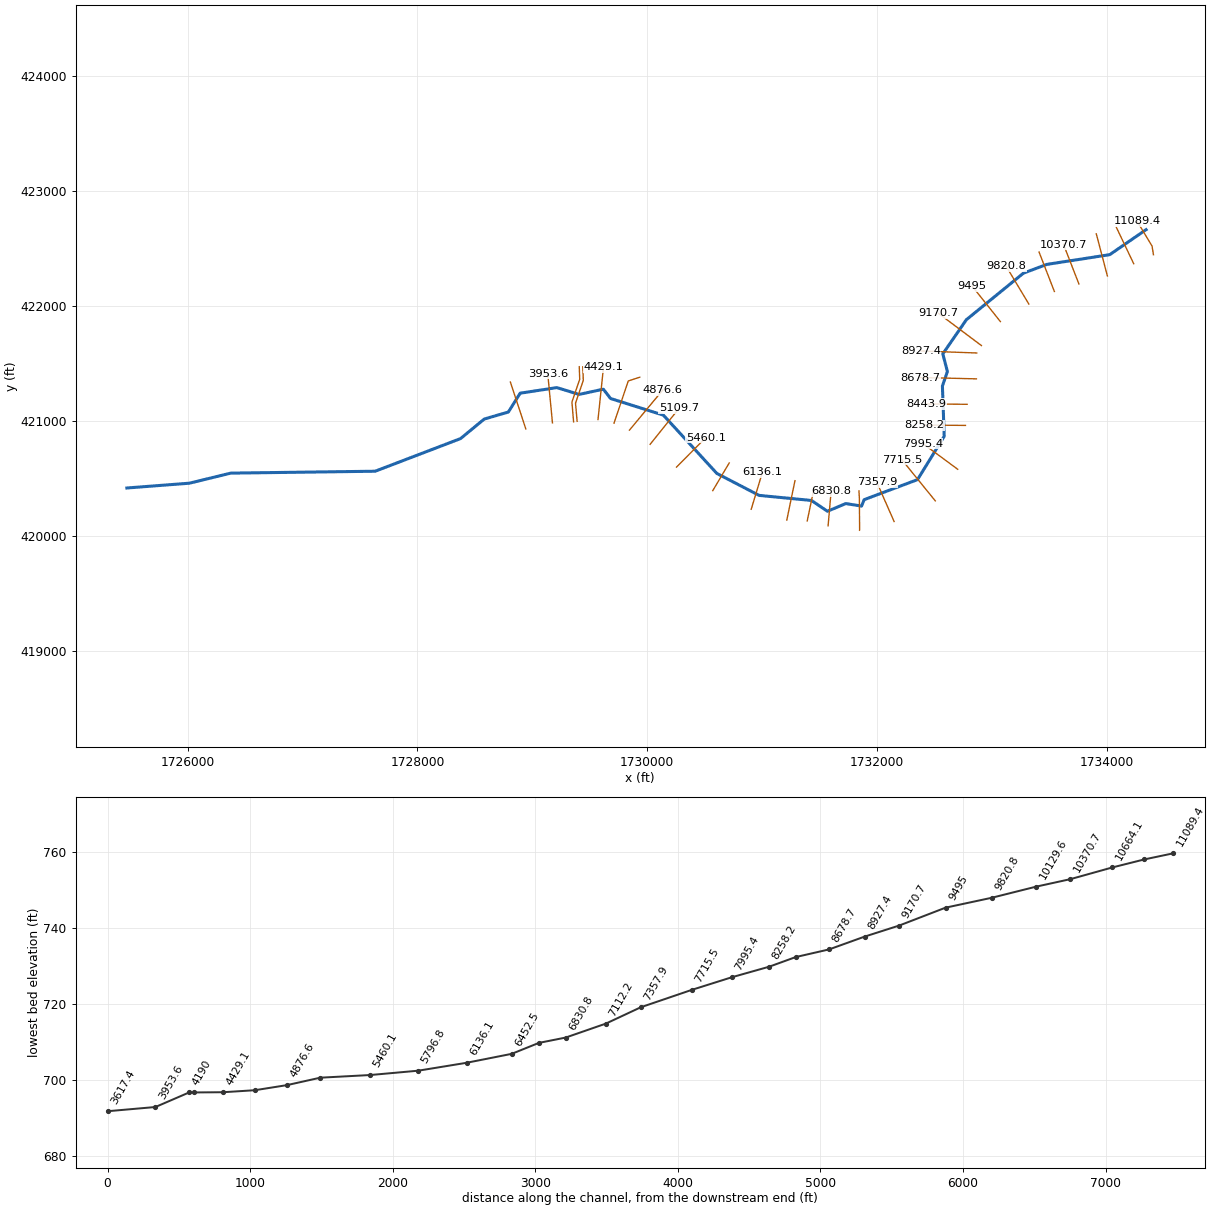
--- HEWITTCK.prj (project) ---

Proj Title=HEWITTCK
Current Plan=p01
Default Exp/Contr=0,0
English Units
Geom File=g01
Flow File=f01
Plan File=p01
BEGIN DESCRIPTION:
END DESCRIPTION:
DSS Export Rating Curves= 0
DSS Export Rating Curve Sorted= 0
DSS Export Volume Flow Curves= 0
DXF OffsetX= 0
DXF OffsetY= 0
DXF ScaleX= 0
DXF ScaleY= 0

--- HEWITTCK.p01 (plan) ---

Plan Title=Floodplain
Program Version=4.00
Geom File=g01
Flow File=f01
K Sum by GR=0
Std Step Tol=0.01
Critical Tol=0.01
Num of Std Step Trials=20
Max Error Tol=0.3
Flow Tol Ratio=0.001
Split Flow NTrial=30
Split Flow Tol=0.02
Split Flow Ratio=0.02
Log Output Level=0
Friction Slope Method=1
Unsteady Friction Slope Method=2
Unsteady Bridges Friction Slope Method=1
Global Log Level=0
CheckData=False
Run HTab=0
Run UNet=0
Run PostProcess=0
UNET Theta=0
UNET Theta Warmup=0
UNET ZTol=0
UNET ZSATol=0
UNET MxIter=0
UNET MaxInSteps=0
UNET DtIC=0
UNET DtMin=0
UNET MaxCRTS=0
UNET WFStab=0
UNET SFStab=0
UNET WFX=0
UNET SFX=0
UNET DSS MLevel=0
UNET DZMax Abort=0
UNET Convert EG Bridges=0
UNET Use Existing IB Tables=0
UNET Froude Limit=0
UNET Froude Power=0
Write IC File=0
Echo Input=False
Echo Output=False
Write Detailed=0

--- HEWITTCK.f01 (steady flow) ---

Flow Title=NFF Regression Equation
Program Version=4.00
Number of Profiles=1
Profile Names=P100yr
River Rch & RM=HEWITTCK,Main      ,11089.4
1000.955
River Rch & RM=HEWITTCK,Main      ,8927.4
1056.109
River Rch & RM=HEWITTCK,Main      ,6830.8
1173.101
River Rch & RM=HEWITTCK,Main      ,4429.1
1269.641
River Rch & RM=HEWITTCK,Main      ,564.4
1394.545
River Rch & RM=HEWITTCK,Main      ,96.9
1396.963
Boundary for River Rch & Prof#=HEWITTCK,Main      ,1
Up Type=0
Dn Type=3
Dn Slope=0.072181

--- HEWITTCK.g01 (geometry) ---

Geom Title=USGS 10m DEM
Program Version=4.10

River Reach=HEWITTCK        ,Main
Reach XY= 30
     1734342.551      422664.477     1734026.326      422447.072
     1733478.585      422362.303     1733274.592      422285.914
     1732778.065      421881.053     1732573.204      421584.178
     1732613.134      421430.532     1732569.732       421304.49
     1732585.356      420867.077      1732352.84      420490.325
     1731888.308      420315.862     1731865.752      420260.265
     1731728.586      420282.008     1731568.864      420215.167
     1731429.975      420308.917     1730974.245      420353.188
      1730606.19       420544.16     1730140.912      421051.105
     1729680.926      421195.992     1729618.343      421276.799
     1729406.667       421231.35     1729213.829      421290.688
     1728894.384      421242.164     1728791.285      421078.046
     1728581.884      421017.337     1728375.287      420847.198
     1727632.232      420563.344     1726375.287      420546.851
     1726015.044      420459.178     1725470.773      420417.511

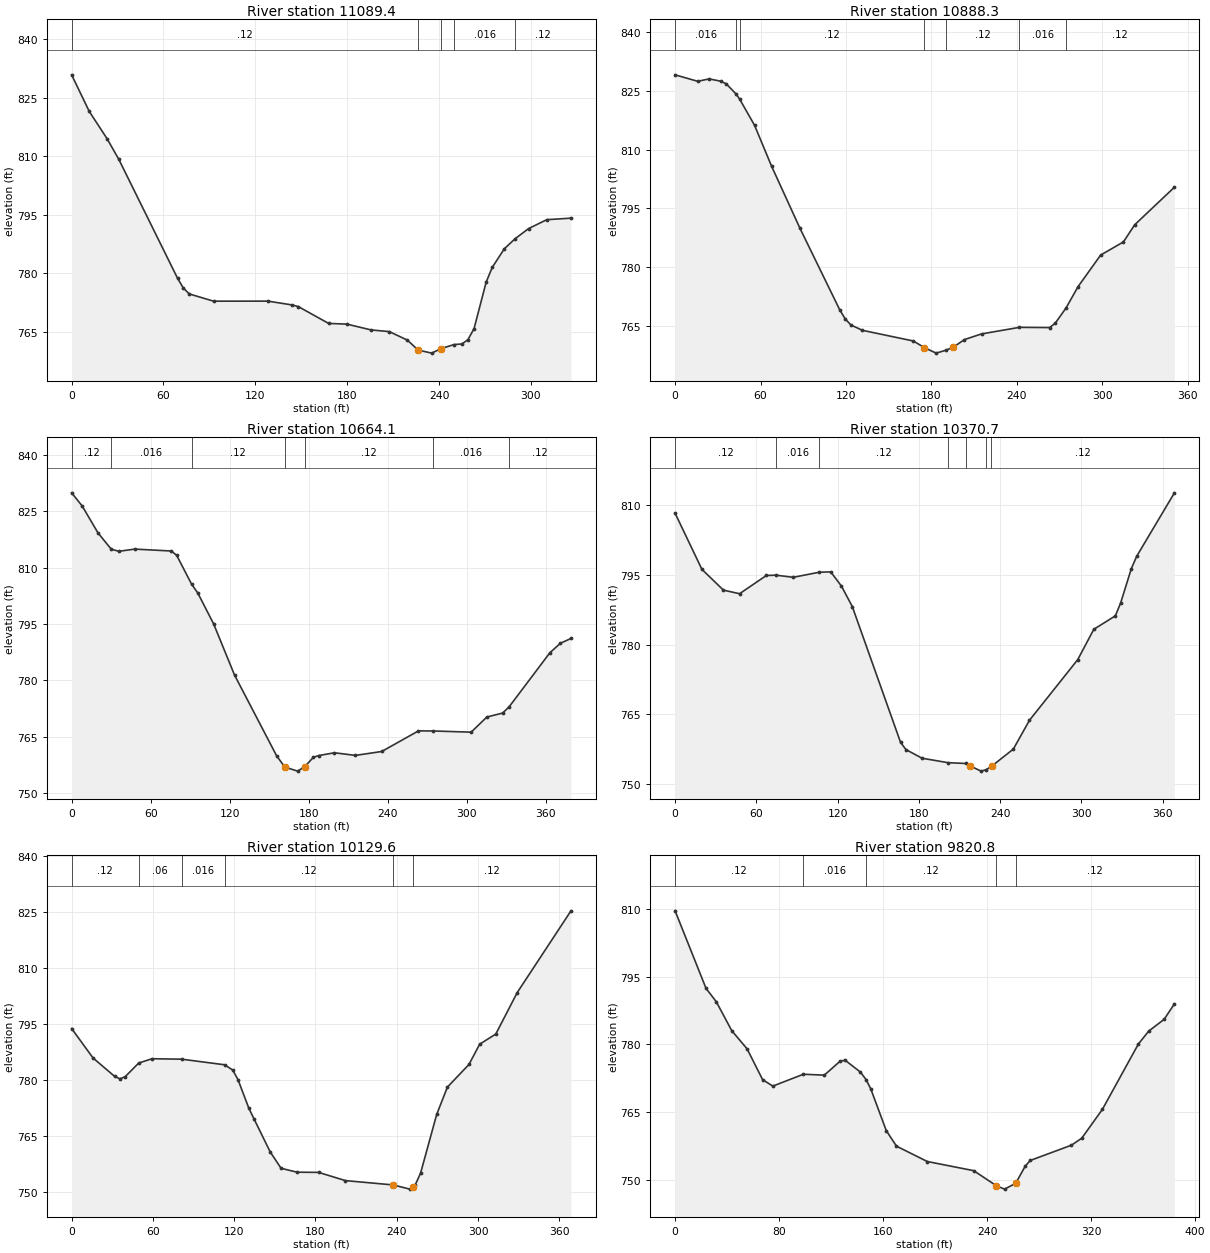
Type RM Length L Ch R = 1 ,11089.4 ,203.4,201,198.6
XS GIS Cut Line= 3
     1734406.772      422446.225     1734394.301      422522.076
     1734265.584       422735.62
#Sta/Elev= 30
       0  830.84    11.5  821.48    23.1  814.52    30.8  809.22    69.2  778.76
      73  776.24    76.9  774.75    92.7   772.9   128.3  772.91   144.2  771.92
   148.1  771.51   167.9   767.2   179.8  767.03   195.6  765.54   207.5  765.11
   219.4  762.92   226.3  760.39   235.2   759.6   241.3  760.76  249.81761.7889
     255  761.95   258.9  763.05   262.9  765.89   270.8  777.78   274.8  781.57
   282.7  786.33  289.76788.9028   298.5  791.48   310.4  793.76   326.2  794.15
#Mann= 5 ,-1 , 0
       0     .12       0   226.3    .045       0   241.3     .12       0
  249.81    .016       0  289.76     .12       0
Bank Sta=226.3,241.3
XS Rating Curve= 0 ,0
Exp/Cntr=0.3,0.1

Type RM Length L Ch R = 1 ,10888.3 ,228.4,224.2,220.2
XS GIS Cut Line= 2
     1734234.897        422368.1     1734083.855      422684.506
#Sta/Elev= 30
       0  829.13    15.9  827.47    23.9  828.09    31.9  827.51    35.9  826.84
    42.9824.1912   45.38822.8917    55.8  816.23    67.7  805.82    87.6  789.97
   115.5  769.15   119.5  766.72   123.5   765.2   131.5  763.84   167.3  761.11
   175.1   759.4   183.3  758.01   190.1  758.75   195.2   759.5   203.2  761.48
   215.2  762.92  241.75764.5963     263  764.54   266.9  765.65  274.48769.5385
   282.9  774.98   298.8  783.07   314.8  786.43   322.7  790.81   350.6  800.41
#Mann= 7 ,-1 , 0
       0    .016       0    42.9      .1       0   45.38     .12       0
   175.1    .045       0   190.1     .12       0  241.75    .016       0
  274.48     .12       0
Bank Sta=175.1,195.2
XS Rating Curve= 0 ,0
Exp/Cntr=0.3,0.1

Type RM Length L Ch R = 1 ,10664.1 ,290.4,293.5,296.2
XS GIS Cut Line= 2
     1734005.751      422261.834     1733909.099      422628.501
#Sta/Elev= 30
       0  829.89       8  826.39      20  819.25   30.07814.9067    35.9  814.34
    47.9  814.93    75.8  814.42    79.8  813.25   91.16805.5752    95.8  803.26
   107.8  795.07   123.7  781.45   155.7  759.95   161.9  756.98   171.6   755.9
   176.9  757.04   183.6  759.57   187.6  760.04   199.6  760.78   215.5  760.08
   235.5  761.12   263.4   766.6  274.43766.5782   303.4  766.26   315.3  770.28
   327.3  771.34  332.25773.0052   363.2  787.38   371.2   789.9   379.2  791.17
#Mann= 7 ,-1 , 0
       0     .12       0   30.07    .016       0   91.16     .12       0
   161.9    .045       0   176.9     .12       0  274.43    .016       0
  332.25     .12       0
Bank Sta=161.9,176.9
XS Rating Curve= 0 ,0
Exp/Cntr=0.3,0.1

Type RM Length L Ch R = 1 ,10370.7 ,241.9,241.1,240.3
XS GIS Cut Line= 2
     1733757.888      422191.714     1733624.312       422535.21
#Sta/Elev= 30
       0  808.21    19.8  796.15    35.7  791.69    47.6  790.92    67.4  794.84
   74.75794.8965    87.2  794.44  106.44795.5336   114.9  795.61   122.8  792.55
   130.8  788.17   166.4  759.03   170.4  757.46   182.3   755.6  201.51 754.643
   214.6  754.47     218  753.91   225.9  752.83   229.6  753.13   233.2753.7985
   233.8  753.91   249.7  757.57   261.6  763.75   297.2  776.76   309.1  783.28
     325  786.17   328.9  788.94   336.8  796.32   340.8  798.99   368.6  812.58
#Mann= 7 ,-1 , 0
       0     .12       0   74.75    .016       0  106.44     .12       0
  201.51    .016       0   214.6    .045       0   229.6    .016       0
   233.2     .12       0
Bank Sta=218,233.8
XS Rating Curve= 0 ,0
Exp/Cntr=0.3,0.1

Type RM Length L Ch R = 1 ,10129.6 ,305.8,308.8,311
XS GIS Cut Line= 2
     1733544.346       422126.61      1733410.77      422470.106
#Sta/Elev= 30
       0  793.83    15.8  785.95    31.7  781.04    35.7  780.36    39.6  780.97
   49.53784.6002    59.4  785.75   81.22785.6251  112.91784.1318   118.9  782.72
   122.8  780.16   130.8  772.51   134.7  769.59   146.6   760.8   154.6  756.43
   166.4  755.38   182.3  755.33   202.1  753.13   237.2  751.98   249.7  750.85
   252.2  751.55   253.6  751.94   257.6  755.15   269.5  770.86   277.4  778.16
   293.3  784.21   301.2  789.63   313.1  792.35   328.9  803.44   368.6  825.33
#Mann= 6 ,-1 , 0
       0     .12       0   49.53     .06       0   81.22    .016       0
  112.91     .12       0   237.2    .045       0   252.2     .12       0
Bank Sta=237.2,252.2
XS Rating Curve= 0 ,0
Exp/Cntr=0.3,0.1

Type RM Length L Ch R = 1 ,9820.8  ,322.4,325.8,328.5
XS GIS Cut Line= 2
     1733322.137      422017.333     1733124.213      422346.545
#Sta/Elev= 30
       0  809.62    23.8  792.44    31.7  789.47    43.6  783.06    55.4  779.03
    67.3  772.22    75.2  770.78   98.69773.4068   114.8  773.21   126.7  776.24
   130.7  776.53   142.6  773.88  146.91772.2173   150.5  770.18   162.4  760.94
   170.3  757.47     194  754.07   229.7  752.04     247  748.72   253.4  747.95
     262  749.23   269.3  753.04   273.2   754.3   304.9  757.69   312.8  759.23
   328.7  765.63   356.4  780.12   364.3  782.96   376.2  785.58   384.1  789.01
#Mann= 5 ,-1 , 0
       0     .12       0   98.69    .016       0  146.91     .12       0
     247    .045       0     262     .12       0
Bank Sta=247,262
XS Rating Curve= 0 ,0
Exp/Cntr=0.3,0.1

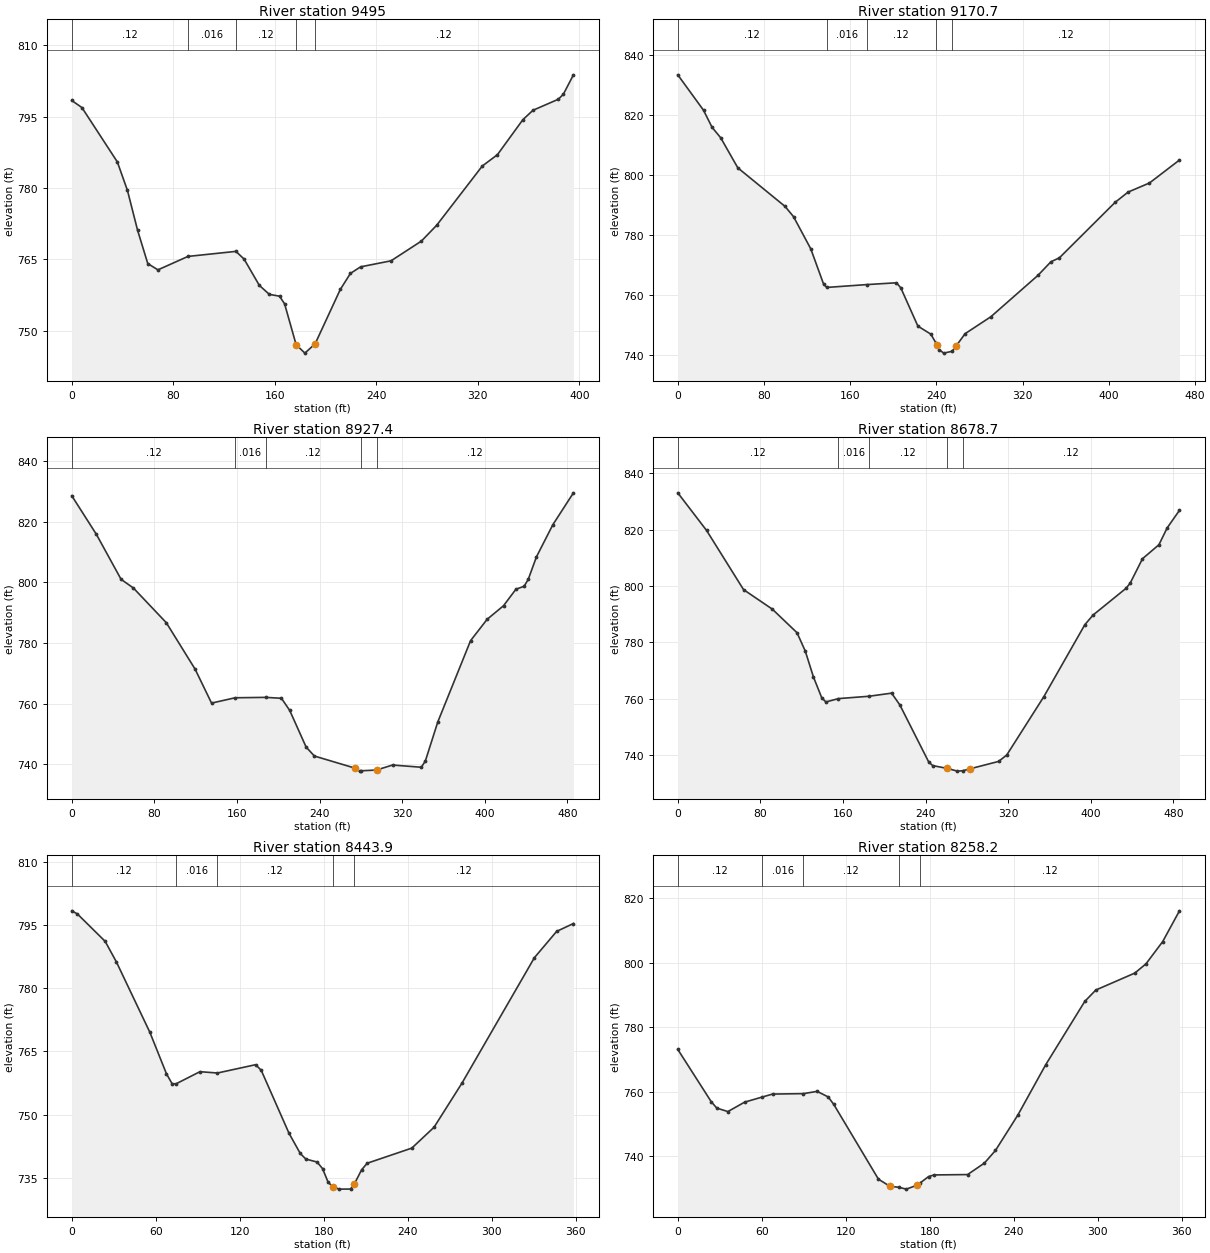
Type RM Length L Ch R = 1 ,9495    ,318.5,324.3,330.1
XS GIS Cut Line= 2
     1733074.314      421864.842     1732827.973      422174.052
#Sta/Elev= 30
       0  798.39       8  796.91    35.9   785.5    43.9  779.49    51.9  771.11
    59.9  764.14    67.9  762.82   91.61765.6419  129.37766.7002   135.8  765.08
   147.8  759.56   155.7  757.67   163.7  757.29   167.7  755.69   176.8  747.11
   183.7  745.33   191.8   747.3   211.6   758.7   219.6  762.08   227.6  763.45
   251.6  764.72   275.5  768.86   287.5  772.17   323.5  784.63   335.4     787
   355.4  794.34   363.4  796.33   383.4  798.65   387.4  799.72   395.3  803.78
#Mann= 5 ,-1 , 0
       0     .12       0   91.61    .016       0  129.37     .12       0
   176.8    .045       0   191.8     .12       0
Bank Sta=176.8,191.8
XS Rating Curve= 0 ,0
Exp/Cntr=0.3,0.1

Type RM Length L Ch R = 1 ,9170.7  ,229,243.3,257.2
XS GIS Cut Line= 2
     1732909.381      421656.361      1732536.72      421935.369
#Sta/Elev= 30
       0  833.37    23.9  821.56    31.8  815.89    39.8  812.41    55.7  802.38
    99.5  789.54   107.4  786.11   123.4  775.39   135.3  763.64  138.24762.5302
  175.13763.4705   202.9  764.08   206.9  762.42   222.8  749.64   234.8  746.97
   239.6  743.98  240.87  743.32   242.7  741.79   246.7  740.64   254.6  741.26
   258.6  743.18   266.6  747.12   290.5  752.76   334.2  766.55   346.2  771.07
   354.1   772.4   405.8  790.88   417.8  794.29   437.7  797.34   465.5  804.98
#Mann= 5 ,-1 , 0
       0     .12       0  138.24    .016       0  175.13     .12       0
   239.6    .045       0   254.6     .12       0
Bank Sta=240.87,258.6
XS Rating Curve= 0 ,0
Exp/Cntr=0.3,0.1

Type RM Length L Ch R = 1 ,8927.4  ,248.7,248.7,250.3
XS GIS Cut Line= 2
     1732868.236      421591.908     1732382.624      421609.168
#Sta/Elev= 30
       0  828.57    23.9   815.8    47.8  800.98    59.7  798.13    91.6  786.67
   119.5  771.34   135.4  760.16  158.22761.9167  187.78762.0484   203.1  761.75
   211.1  757.75     227  745.66     235   742.7   274.8  738.66   278.8  737.72
   280.2  737.83   295.2  738.08   310.7  739.73   338.6     739   342.5  741.08
   354.5  753.92   386.3  780.77   402.3  787.79   418.2  792.28   430.2  797.72
   438.1  798.69   442.1  800.94   450.1  808.41     466  819.02   485.9  829.52
#Mann= 5 ,-1 , 0
       0     .12       0  158.22    .016       0  187.78     .12       0
   280.2    .045       0   295.2     .12       0
Bank Sta=274.8,295.2
XS Rating Curve= 0 ,0
Exp/Cntr=0.3,0.1

Type RM Length L Ch R = 1 ,8678.7  ,234.2,234.8,233.6
XS GIS Cut Line= 2
     1732865.716      421366.879     1732379.936      421378.468
#Sta/Elev= 30
       0  833.03    27.9  819.69    63.7  798.71    91.6  791.78   115.5  783.43
   123.5  776.91   131.4  767.74   139.4   760.4   143.4  758.88  155.65760.0746
  185.19760.9049   207.1  762.01   215.1  757.82     243  737.63   246.9  736.32
     261  735.33   270.8  734.36     276   734.5   282.8  735.16   310.7   737.8
   318.6  740.06   354.5  760.73   394.3   786.3   402.3  789.72   434.1  799.16
   438.1  800.96   450.1  809.67     466  814.62     474   820.6   485.9  826.82
#Mann= 5 ,-1 , 0
       0     .12       0  155.65    .016       0  185.19     .12       0
     261    .045       0     276     .12       0
Bank Sta=261,282.8
XS Rating Curve= 0 ,0
Exp/Cntr=0.3,0.1

Type RM Length L Ch R = 1 ,8443.9  ,185.6,185.7,185.5
XS GIS Cut Line= 2
     1732784.689      421145.422     1732426.222      421148.349
#Sta/Elev= 30
       0  798.36       4  797.63    23.9  791.11    31.9  786.24    55.8  769.56
    67.7  759.69    71.7  757.35   74.58757.3284    91.6   760.2  104.12759.8867
   131.4  761.86   135.4  760.53   155.3  745.56   163.3   740.8   167.3  739.47
   175.3  738.77   179.2  737.22   183.2  733.98   186.8  732.81   191.2  732.34
   199.2  732.36   201.8  733.46   207.1  736.91   211.1  738.48     243  742.07
   258.9  747.02   278.8  757.46   330.6  787.24   346.5  793.48   358.5  795.35
#Mann= 5 ,-1 , 0
       0     .12       0   74.58    .016       0  104.12     .12       0
   186.8    .045       0   201.8     .12       0
Bank Sta=186.8,201.8
XS Rating Curve= 0 ,0
Exp/Cntr=0.3,0.1

Type RM Length L Ch R = 1 ,8258.2  ,276.9,262.8,248.5
XS GIS Cut Line= 2
     1732770.366      420961.828     1732411.899      420964.755
#Sta/Elev= 30
       0   773.1    23.9   756.9    27.9  754.91    35.8  753.84    47.8  756.77
   60.26758.3331    67.7  759.26   89.79 759.399    99.6   760.1   107.5  758.37
   111.5  756.04   143.4  732.89   151.4  730.74   158.2  730.35   163.3  729.81
   171.3  731.07   173.2  731.72   179.2   733.7   183.2  734.21   207.1  734.32
   219.1  737.87     227  741.78     243  752.75   262.9  768.34   290.8  787.95
   298.7  791.49   326.6  796.75   334.6  799.63   346.5   806.5   358.5  816.04
#Mann= 5 ,-1 , 0
       0     .12       0   60.26    .016       0   89.79     .12       0
   158.2    .045       0   173.2     .12       0
Bank Sta=151.4,171.3
XS Rating Curve= 0 ,0
Exp/Cntr=0.3,0.1

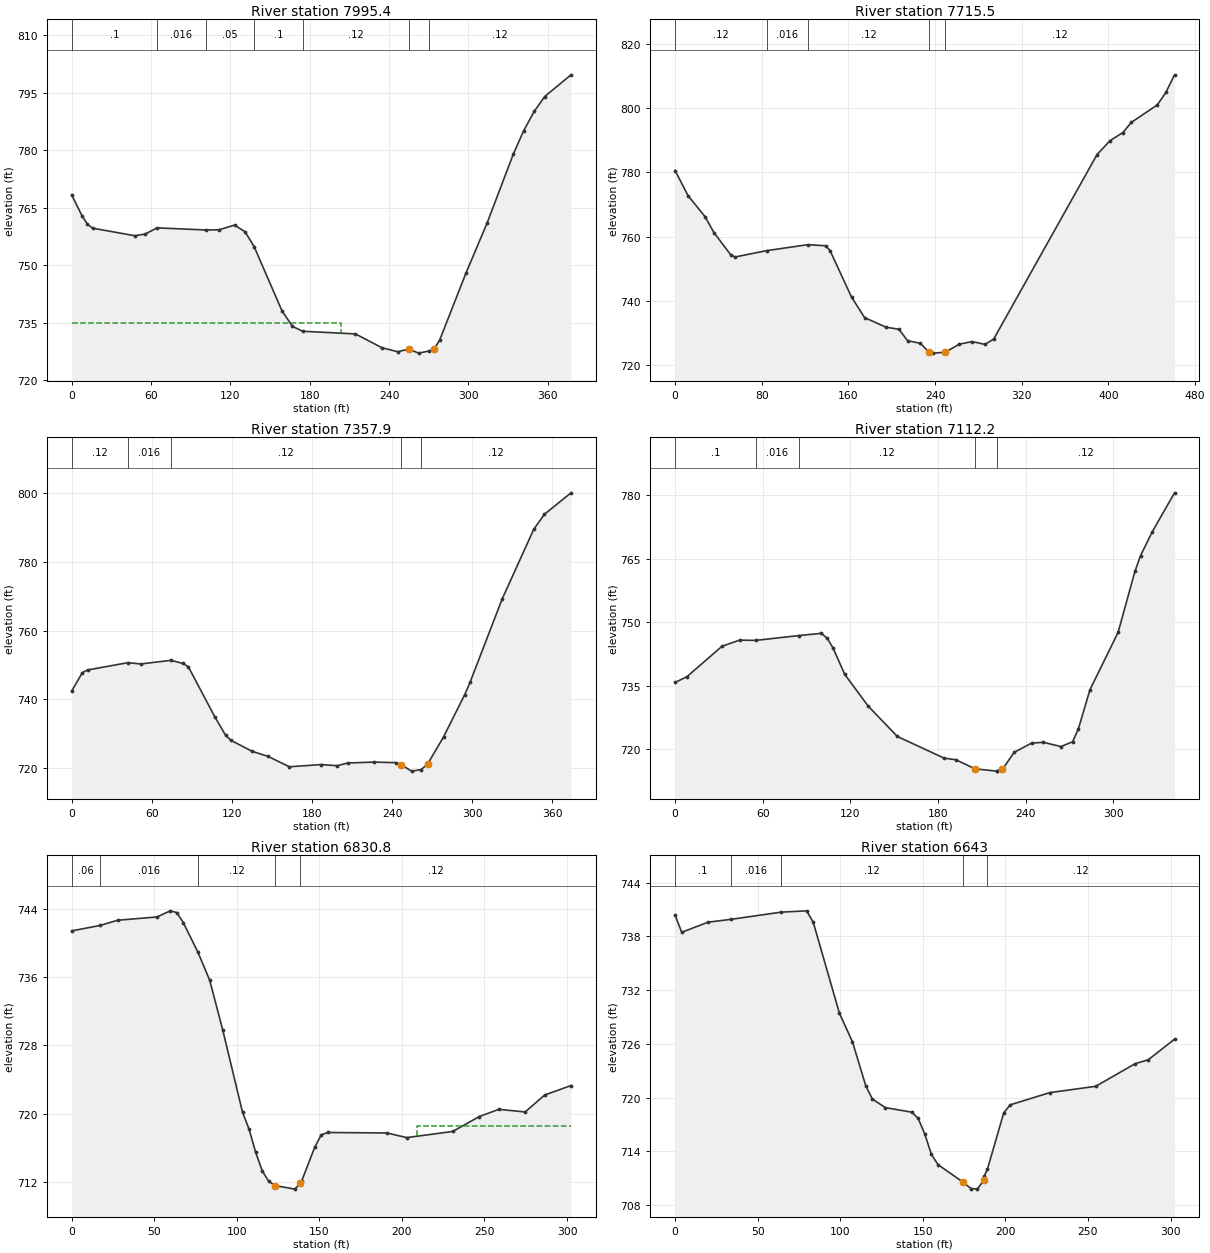
Type RM Length L Ch R = 1 ,7995.4  ,285.8,279.9,274.1
XS GIS Cut Line= 2
     1732703.003      420580.258      1732399.16      420804.426
#Sta/Elev= 30
       0  768.33       8  762.75    11.9  760.66    15.9  759.62    47.7  757.65
    55.6  758.08   64.58 759.701  101.28759.1496   111.3  759.19   123.2  760.42
   131.2  758.66  137.98 754.816     159   738.1   166.9  734.03  174.69732.7336
   214.6  732.04   234.5  728.46   246.4   727.4   255.1  728.07   262.3  727.03
   270.1  727.57   274.2  728.17   278.2  730.36   298.1  747.84     314  760.84
   333.9  778.86   341.8  785.04   349.8  790.08   357.7  793.95   377.6  799.61
#Mann= 7 ,-1 , 0
       0      .1       0   64.58    .016       0  101.28     .05       0
  137.98      .1       0  174.69     .12       0   255.1    .045       0
   270.1     .12       0
#XS Ineff= 2 , 0
          203.93     735
Permanent Ineff=
       F       F
Bank Sta=255.1,274.2
XS Rating Curve= 0 ,0
Exp/Cntr=0.3,0.1

Type RM Length L Ch R = 1 ,7715.5  ,362.2,357.6,352.1
XS GIS Cut Line= 2
       1732507.6      420305.649     1732216.841      420663.386
#Sta/Elev= 30
       0  780.54    11.9  772.74    27.8  766.11    35.8  761.25    51.7  754.14
    55.6  753.66   84.38755.6132  122.44757.4753   139.1  757.13   143.1  755.56
   162.9  741.13   174.9  734.77   194.7  731.78   206.6  731.15   214.6  727.59
   226.5  726.76   234.4  724.01   238.4  723.72   249.4  724.01   262.3  726.49
   274.2  727.32   286.1  726.43   294.1  728.12   389.5  785.53   401.4  789.83
   413.3  792.37   421.2  795.55   445.1  800.97     453  804.85     461  810.34
#Mann= 5 ,-1 , 0
       0     .12       0   84.38    .016       0  122.44     .12       0
   234.4    .045       0   249.4     .12       0
Bank Sta=234.4,249.4
XS Rating Curve= 0 ,0
Exp/Cntr=0.3,0.1

Type RM Length L Ch R = 1 ,7357.9  ,255.4,245.7,229.6
XS GIS Cut Line= 2
     1732149.272       420125.89     1731998.397      420468.093
#Sta/Elev= 30
       0  742.41       8  747.78    11.9  748.56   42.07750.6873    51.7  750.31
   74.35751.3713    83.6  750.45    87.5  749.43   107.4  734.81   115.4  729.53
   119.4  728.07   135.3   724.9   147.2  723.42   163.1  720.41     187  721.06
   198.9  720.73   206.9  721.52   226.8  721.78   242.7  721.61   246.8     721
   254.6  719.15   261.8  719.61   266.6  721.21   278.5  729.07   294.4   741.4
   298.4  744.98   322.3  769.09   346.1  789.48   354.1  793.84     374  800.08
#Mann= 5 ,-1 , 0
       0     .12       0   42.07    .016       0   74.35     .12       0
   246.8    .045       0   261.8     .12       0
Bank Sta=246.8,266.6
XS Rating Curve= 0 ,0
Exp/Cntr=0.3,0.1

Type RM Length L Ch R = 1 ,7112.2  ,285.6,281.4,277.5
XS GIS Cut Line= 4
     1731848.968      420050.155     1731849.069      420050.277
     1731846.798      420330.173     1731843.064      420391.779
#Sta/Elev= 30
       0  735.76     8.1  737.14    32.1  744.31    44.1  745.75    55.2745.6953
   84.73746.8362   100.1  747.36   104.1  746.19   108.1  743.88   116.1  737.67
   132.1   730.2   152.1  723.02   184.1  717.91   192.1  717.53   205.3  715.38
     220  714.84   220.3  714.87     224  715.23     232  719.27     244  721.46
     252  721.64     264  720.64     272  721.76     276  724.81   283.9  734.03
   303.2   747.6   314.7  761.98   318.6  765.72   326.3  771.16   341.8  780.52
#Mann= 5 ,-1 , 0
       0      .1       0    55.2    .016       0   84.73     .12       0
   205.3    .045       0   220.3     .12       0
Bank Sta=205.3,224
XS Rating Curve= 0 ,0
Exp/Cntr=0.3,0.1

Type RM Length L Ch R = 1 ,6830.8  ,188,187.8,185.9
XS GIS Cut Line= 2
      1731574.62      420088.153     1731601.048      420389.424
#Sta/Elev= 30
       0   741.4   17.23742.0397    27.9  742.65    51.7  743.03    59.7  743.75
    63.7  743.55    67.6  742.38   76.53738.8834    83.6  735.63    91.5  729.81
   103.5  720.16   107.4  718.22   111.4  715.52   115.4  713.32   119.4  712.08
   123.2  711.59   135.3  711.18   138.2  711.87   139.3  712.13   147.2  716.08
   151.2  717.54   155.2  717.81     191  717.75   202.9  717.21   230.8  717.93
   246.7  719.66   258.7  720.52   274.6  720.21   286.5   722.2   302.4   723.3
#Mann= 5 ,-1 , 0
       0     .06       0   17.23    .016       0   76.53     .12       0
   123.2    .045       0   138.2     .12       0
#XS Ineff= 2 , 0
                          209.41          718.57
Permanent Ineff=
       F       F
Bank Sta=123.2,138.2
XS Rating Curve= 0 ,0
Exp/Cntr=0.3,0.1

Type RM Length L Ch R = 1 ,6643    ,189.7,190.6,190.8
XS GIS Cut Line= 2
     1731393.055      420131.092     1731454.488      420427.214
#Sta/Elev= 30
       0  740.34       4  738.45    19.9  739.58   34.01739.9039   64.17740.7017
    79.6  740.85    83.6  739.59    99.5  729.41   107.4  726.22   115.4  721.34
   119.4  719.84   127.3  718.88   143.3  718.37   147.2  717.67   151.2  715.92
   155.2  713.65   159.2  712.51   174.1  710.59   179.1  709.85     183  709.78
     187   710.8  187.29  711.28   189.1  712.01     199   718.3   202.9  719.19
   226.8  720.55   254.7  721.26   278.6  723.79   286.5  724.22   302.4  726.52
#Mann= 5 ,-1 , 0
       0      .1       0   34.01    .016       0   64.17     .12       0
   174.1    .045       0   189.1     .12       0
Bank Sta=174.1,187
XS Rating Curve= 0 ,0
Exp/Cntr=0.3,0.1

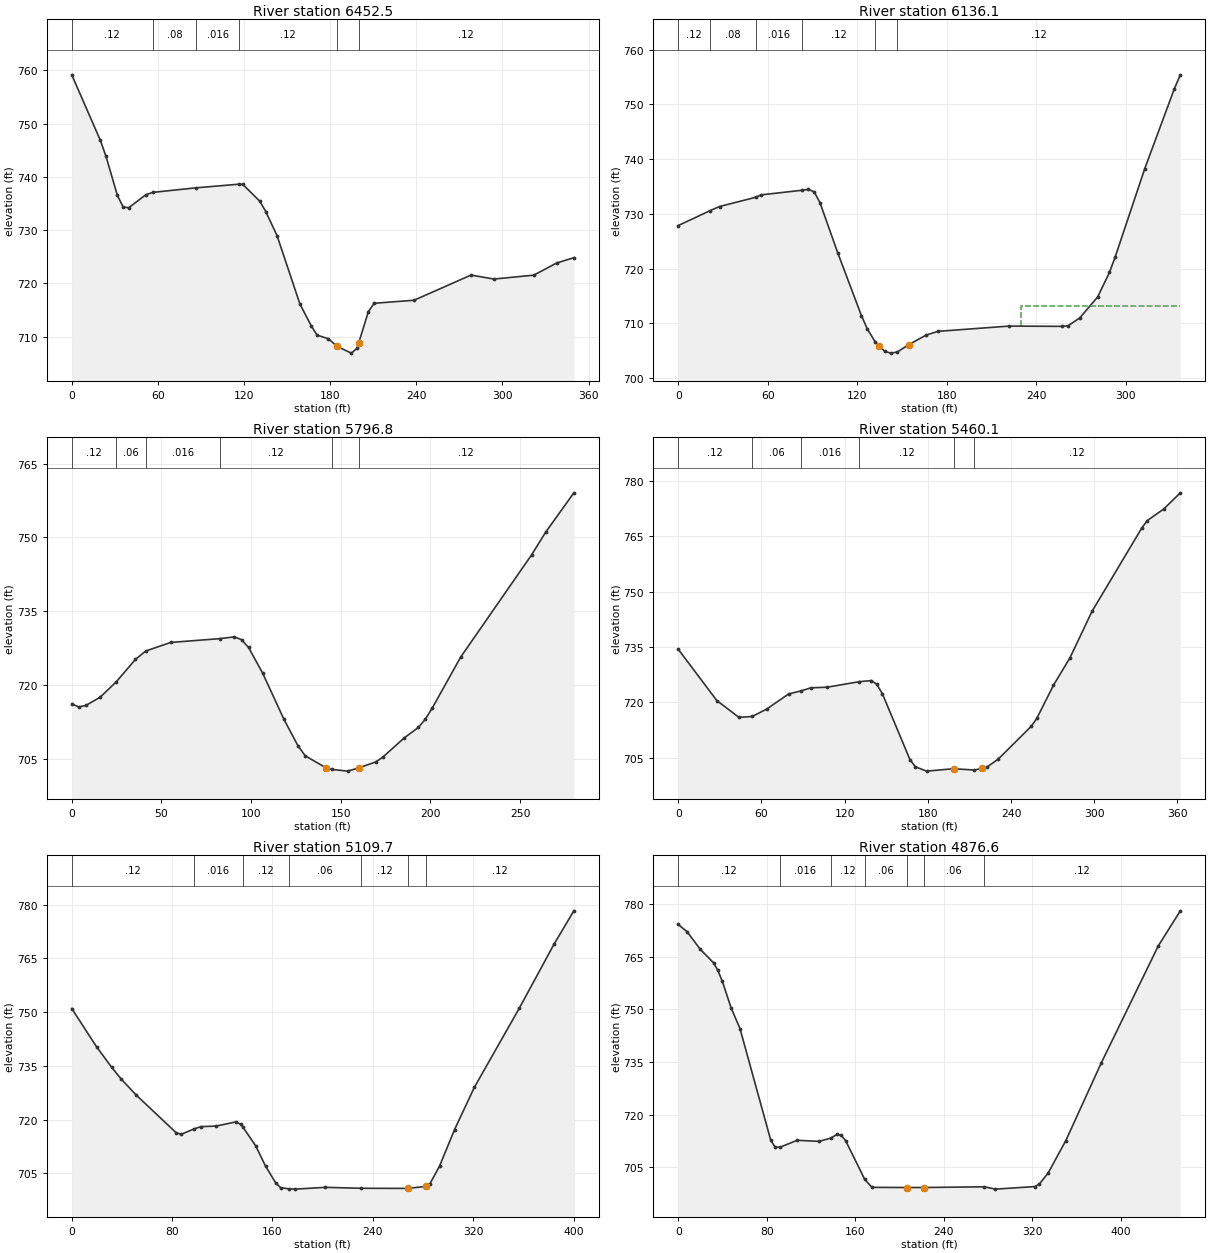
Type RM Length L Ch R = 1 ,6452.5  ,318.3,316.3,314
XS GIS Cut Line= 2
     1731215.214      420138.662     1731286.118      420481.059
#Sta/Elev= 30
       0  759.16    19.9  746.87    23.8  743.88    31.8   736.5    35.8  734.34
    39.7  734.21    51.6  736.65   56.44737.0862    86.6 737.944  116.76 738.631
   119.2  738.57   131.1  735.39   135.1  733.49     143  728.95   158.9  716.13
   166.9  711.98   170.9  710.28   178.8   709.6   184.8  708.17   194.7   706.9
   198.7  707.81   199.8  708.77   206.6   714.7   210.6  716.26   238.4  716.83
   278.1  721.56     294  720.81   321.8  721.54   337.7  723.82   349.7  724.82
#Mann= 6 ,-1 , 0
       0     .12       0   56.44     .08       0    86.6    .016       0
  116.76     .12       0   184.8    .045       0   199.8     .12       0
Bank Sta=184.8,199.8
XS Rating Curve= 0 ,0
Exp/Cntr=0.3,0.1

Type RM Length L Ch R = 1 ,6136.1  ,345,339.4,333.9
XS GIS Cut Line= 2
     1730905.401      420232.618     1731003.319      420554.673
#Sta/Elev= 30
       0  727.85    21.3  730.57    27.7  731.33   52.17733.0276    55.4  733.45
   83.04734.3016    87.1  734.46    91.1  734.03      95  732.04   106.9   722.9
   122.8  711.41   126.7     709   131.9  706.67   134.6  705.88   138.6  704.86
   142.6  704.55   146.9  704.76   154.4  706.08   166.3  707.86   174.2  708.53
   221.8  709.49   257.4  709.44   261.4  709.55   269.3  711.01   281.2  714.82
   289.1  719.29     293  722.17   312.8  738.27   332.6  752.84   336.6  755.38
#Mann= 6 ,-1 , 0
       0     .12       0    21.3     .08       0   52.17    .016       0
   83.04     .12       0   131.9    .045       0   146.9     .12       0
#XS Ineff= 2 , 0
                          230.06          713.24
Permanent Ineff=
       F       F
Bank Sta=134.6,154.4
XS Rating Curve= 0 ,0
Exp/Cntr=0.3,0.1

Type RM Length L Ch R = 1 ,5796.8  ,342.4,336.7,331.3
XS GIS Cut Line= 2
     1730570.897       420394.77     1730714.072      420635.425
#Sta/Elev= 30
       0  716.15     3.9  715.52     7.9  715.83    15.8  717.49   24.79720.6135
    35.5  725.18   41.24726.8849    55.2  728.63   82.55 729.399    90.7  729.76
    94.7  729.18    98.6   727.6   106.5  722.36   118.3  713.02   126.2  707.59
   130.2  705.59     142  703.09     145  702.82   153.8  702.47     160  703.12
   169.6  704.35   173.5  705.33   185.4  709.22   193.3  711.35   197.2  713.04
   201.1  715.33   216.9  725.66   256.4  746.41   264.2  750.99     280  759.04
#Mann= 6 ,-1 , 0
       0     .12       0   24.79     .06       0   41.24    .016       0
   82.55     .12       0     145    .045       0     160     .12       0
Bank Sta=142,160
XS Rating Curve= 0 ,0
Exp/Cntr=0.3,0.1

Type RM Length L Ch R = 1 ,5460.1  ,349.2,350.3,349.7
XS GIS Cut Line= 2
     1730255.245      420599.087     1730510.275      420856.151
#Sta/Elev= 30
       0  734.38    27.8  720.48    43.8   715.9   53.35716.1556    63.7  718.14
    79.6  722.26   88.76723.1006    95.5  723.92   107.4  724.09  130.69725.5971
   139.3  725.89   143.2  724.88   147.2  722.34   167.1  704.47   171.1  702.49
   179.1  701.33   198.6  701.98   213.6  701.63   218.9  702.06   222.8  702.47
   230.8   704.6   254.7  713.53   258.6  715.64   270.6  724.61   282.5  732.05
   298.4  744.64   334.2   767.2   338.2  769.25   350.2  772.43   362.1   776.8
#Mann= 6 ,-1 , 0
       0     .12       0   53.35     .06       0   88.76    .016       0
  130.69     .12       0   198.6    .045       0   213.6     .12       0
Bank Sta=198.6,218.9
XS Rating Curve= 0 ,0
Exp/Cntr=0.3,0.1

Type RM Length L Ch R = 1 ,5109.7  ,233.2,233.1,232.5
XS GIS Cut Line= 2
     1730025.376      420797.461     1730276.282      421109.212
#Sta/Elev= 30
       0     751    19.8  740.31    31.7  734.66    39.6  731.25    51.5  726.82
    83.2  716.37    87.2  715.92   97.28717.3986     103  718.06   114.9  718.21
   130.8  719.38   134.7  718.69  136.58717.8487   146.6  712.71   154.5  707.03
   162.4  702.46   166.4  701.05   173.1700.7031   178.3  700.63   202.1  701.13
   230.8700.8675   267.7  700.83   282.7  701.41   285.3     702   293.2   707.1
   305.1  717.22   320.9  729.02   356.6  751.02   384.3  768.88   400.2  778.25
#Mann= 7 ,-1 , 0
       0     .12       0   97.28    .016       0  136.58     .12       0
   173.1     .06       0   230.8     .12       0   267.7    .045       0
   282.7     .12       0
Bank Sta=267.7,282.7
XS Rating Curve= 0 ,0
Exp/Cntr=0.3,0.1

Type RM Length L Ch R = 1 ,4876.6  ,216.2,224.5,233.2
XS GIS Cut Line= 2
     1729845.524      420920.838       1730135.8       421269.84
#Sta/Elev= 30
       0  774.29       8  772.22    19.9  767.21    31.9  763.36    35.8  761.17
    39.8  758.11    47.8  750.46    55.8  744.56    83.6  712.69    87.6  710.68
   91.86710.6324   107.5  712.63   127.4  712.33  138.05713.2675   143.4  714.31
   147.3  714.04   151.3  712.55  168.59701.4607   175.2  699.19   207.1  699.14
   222.1  699.14  276.61699.3472   286.7  698.68   322.5  699.41   326.5  700.14
   334.5  703.33   350.4  712.56   382.3  734.65     434  768.18   453.9  778.19
#Mann= 7 ,-1 , 0
       0     .12       0   91.86    .016       0  138.05     .12       0
  168.59     .06       0   207.1    .045       0   222.1     .06       0
  276.61     .12       0
Bank Sta=207.1,222.1
XS Rating Curve= 0 ,0
Exp/Cntr=0.3,0.1

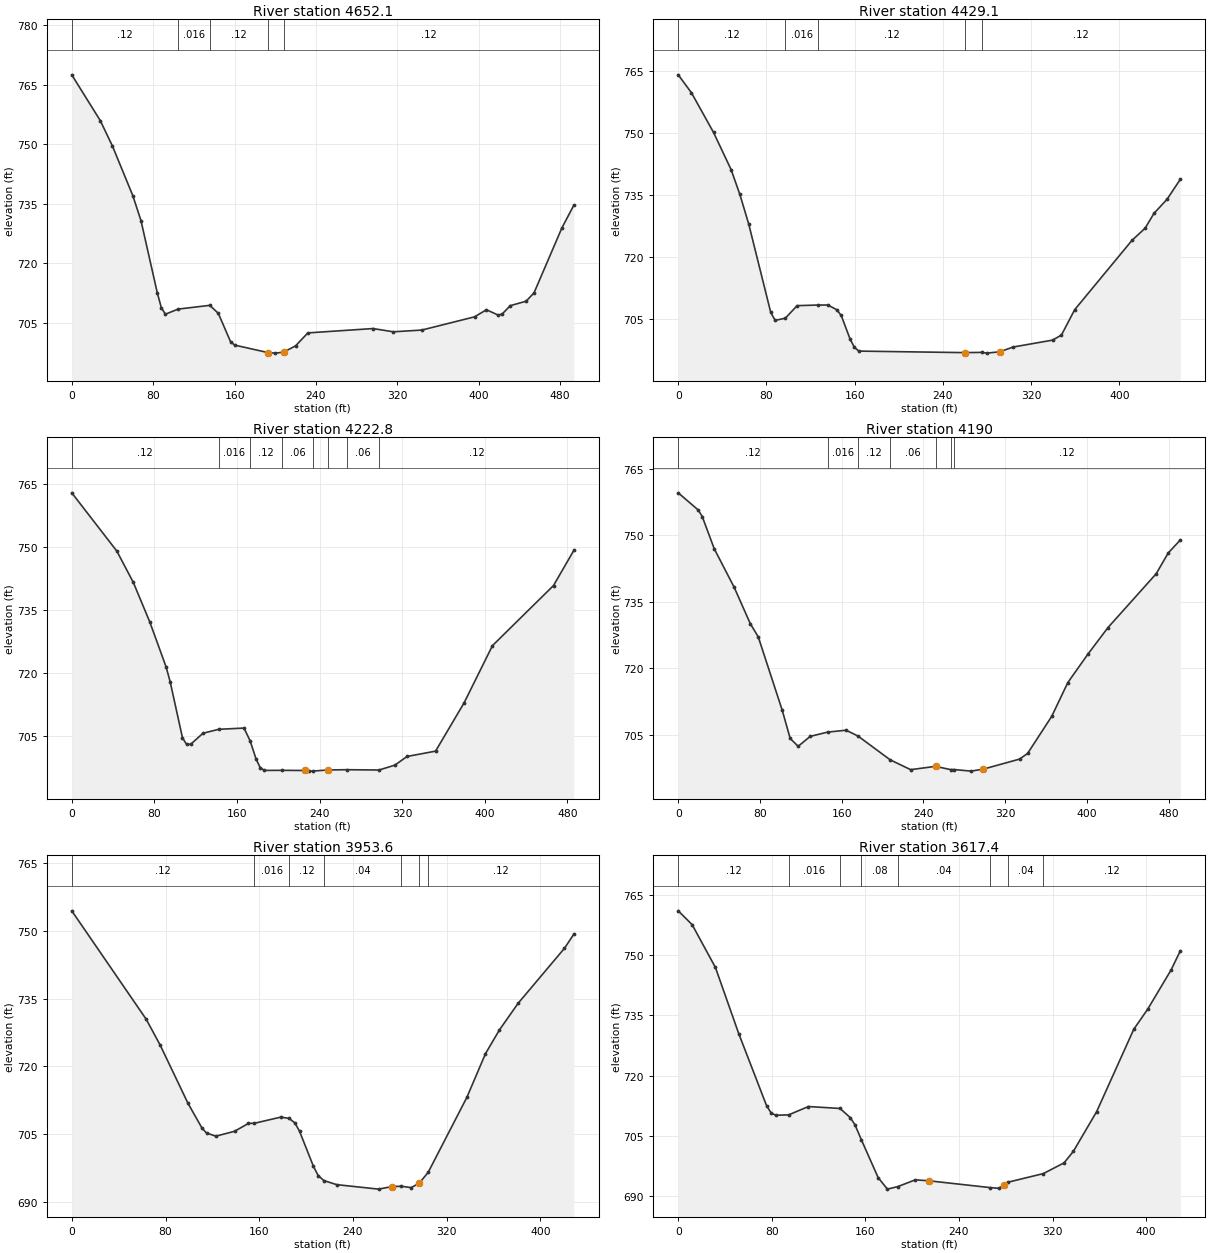
Type RM Length L Ch R = 1 ,4652.1  ,217.7,223,228.2
XS GIS Cut Line= 3
     1729711.086      420980.981     1729835.158      421348.568
     1729935.418       421381.12
#Sta/Elev= 30
       0  767.54      28     756      40  749.56      60  737.06      68  730.78
      84  712.59      88  708.81      92  707.16   104.5708.4437  135.67709.3934
     144  707.38     156  700.25     160  699.37   193.3  697.45     200  697.34
   208.3  697.59     220  699.19     232  702.44     296  703.54     316  702.72
     344  703.16   395.8  706.49   407.5  708.28   419.2  706.92   423.1  707.24
   430.9  709.31   446.5  710.44   454.3  712.56   481.7  728.95   493.4  734.66
#Mann= 5 ,-1 , 0
       0     .12       0   104.5    .016       0  135.67     .12       0
   193.3    .045       0   208.3     .12       0
Bank Sta=193.3,208.3
XS Rating Curve= 0 ,0
Exp/Cntr=0.3,0.1

Type RM Length L Ch R = 1 ,4429.1  ,211.8,206.3,200.9
XS GIS Cut Line= 2
     1729571.842      421012.898     1729619.324      421465.734
#Sta/Elev= 30
       0  764.12      12  759.78      32  750.19    47.9  741.22    55.9  735.18
    63.9  728.05    83.9  706.64    87.9  704.73   97.16 705.266   107.8  708.29
  126.85708.4449   135.8  708.44   143.8   707.3   147.8  705.92   155.8  700.24
   159.8  698.19   163.8   697.3   260.1  696.93   275.1  696.99   279.6  696.81
   291.6  697.13   303.6  698.28   339.5  699.96   347.5  701.18   359.5  707.31
   411.4  724.06   423.4  727.03   431.4   730.6   443.3  734.03   455.3  738.85
#Mann= 5 ,-1 , 0
       0     .12       0   97.16    .016       0  126.85     .12       0
   260.1    .045       0   275.1     .12       0
Bank Sta=260.1,291.6
XS Rating Curve= 0 ,0
Exp/Cntr=0.3,0.1

Type RM Length L Ch R = 1 ,4222.8  ,32.9,32.8,32.9
XS GIS Cut Line= 4
     1729389.938      420997.266     1729376.088      421155.556
     1729443.796      421353.473     1729439.257      421471.499
#Sta/Elev= 30
       0     763    43.7  749.11    59.6  741.67    75.5  732.29    91.4  721.52
    95.3     718   107.2  704.69   111.2  703.11   115.2  703.16   127.1  705.77
  142.34706.7066   166.8     707  172.68703.9791   178.6  699.54   182.6  697.55
   186.5  696.92  203.89696.9399     226   696.9   229.9  696.75   233.4  696.76
   248.4  697.03  266.33697.0898  297.54697.0146   312.8  698.17   324.7  700.24
   352.3  701.51   379.9     713   407.4  726.63   466.5  740.93   486.2   749.3
#Mann= 8 ,-1 , 0
       0     .12       0  142.34    .016       0  172.68     .12       0
  203.89     .06       0   233.4    .045       0   248.4     .08       0
  266.33     .06       0  297.54     .12       0
Bank Sta=226,248.4
XS Rating Curve= 0 ,0
Exp/Cntr=0.3,0.1

Type RM Length L Ch R = 1 ,4190    ,226.1,236.4,246.9
XS GIS Cut Line= 4
       1729359.2      420993.274     1729344.838      421164.931
     1729412.546      421362.848      1729408.67      421472.819
#Sta/Elev= 30
       0  759.54    19.6  755.66    23.5  754.19    35.2  746.94    54.8  738.21
    70.5  730.04    78.3  727.06   101.8  710.49   109.6  704.12   117.4  702.35
   129.2  704.59   146.3705.5563   164.4  705.98  176.13 704.642  207.35 699.318
   227.5  697.08   251.9  697.83   266.9  697.08  269.78697.1088   286.7  696.75
   298.6   697.2   334.1  699.46     342  700.74   365.6   709.1   381.4  716.74
   401.1  723.16   420.7  729.14   467.9  741.29   479.7  745.98   491.5   748.9
#Mann= 7 ,-1 , 0
       0     .12       0   146.3    .016       0  176.13     .12       0
  207.35     .06       0   251.9    .045       0   266.9     .06       0
  269.78     .12       0
Bank Sta=251.9,298.6
XS Rating Curve= 0 ,0
Exp/Cntr=0.3,0.1

Type RM Length L Ch R = 1 ,3953.6  ,330.4,336.2,338.6
XS GIS Cut Line= 2
     1729175.314      420983.963     1729134.342      421410.468
#Sta/Elev= 30
       0  754.37    63.5  730.44    75.4  724.75    99.2  711.86   111.1  706.42
     115  705.31     123  704.61   138.9  705.69   150.8  707.43  155.82707.4588
   178.5  708.83  185.49708.5311   190.4  707.55   194.4   705.7   206.3  697.92
   210.3  695.92  215.16 694.808   226.1  693.91   261.8  692.92   273.7   693.5
   281.4  693.55   289.6  693.26   296.4  694.18  304.17696.6213   337.2  713.18
   353.1  722.84     365  728.08   380.9  733.94   420.5   746.1   428.5  749.22
#Mann= 7 ,-1 , 0
       0     .12       0  155.82    .016       0  185.49     .12       0
  215.16     .04       0   281.4    .045       0   296.4     .04       0
  304.17     .12       0
Bank Sta=273.7,296.4
XS Rating Curve= 0 ,0
Exp/Cntr=0.3,0.1

Type RM Length L Ch R = 1 ,3617.4  ,359.7,362.8,367.6
XS GIS Cut Line= 2
     1728943.369      420931.301     1728809.055       421338.93
#Sta/Elev= 30
       0  760.97    11.9  757.53    31.8  746.89    51.7  730.47    75.5  712.56
    79.5  710.71    83.4  710.17   94.36710.2592   111.3  712.34  138.36711.8539
     147  709.59     151  707.85  156.56704.0709   170.9  694.67   178.8  691.81
  187.66692.4375   202.7  694.12   214.6  693.87   266.6  692.19   274.2  692.01
   278.2  692.78   281.6  693.51  312.04695.6649   329.8  698.33   337.8  701.21
   357.7  711.08   389.4  731.53   401.4  736.57   421.2  746.22   429.2  751.02
#Mann= 8 ,-1 , 0
       0     .12       0   94.36    .016       0  138.36     .12       0
  156.56     .08       0  187.66     .04       0   266.6    .045       0
   281.6     .04       0  312.04     .12       0
Bank Sta=214.6,278.2
XS Rating Curve= 0 ,0
Exp/Cntr=0.3,0.1