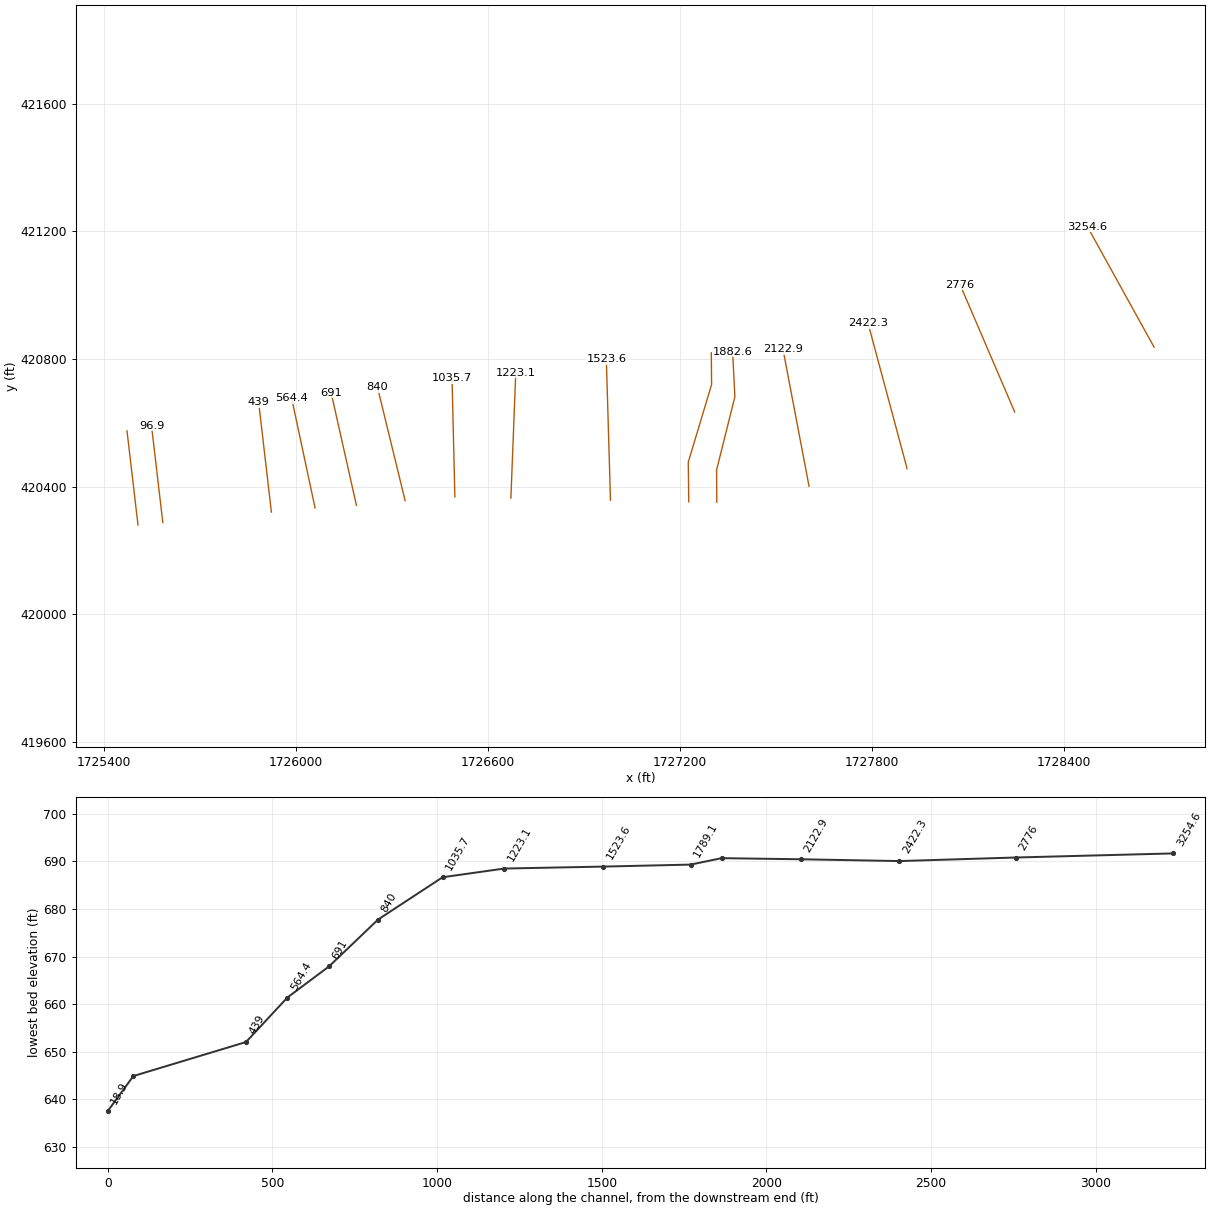
HEC-RAS study HEWITTCK.prj: HEWITTCK

--- HEWITTCK.g01 (geometry) --- (continued)

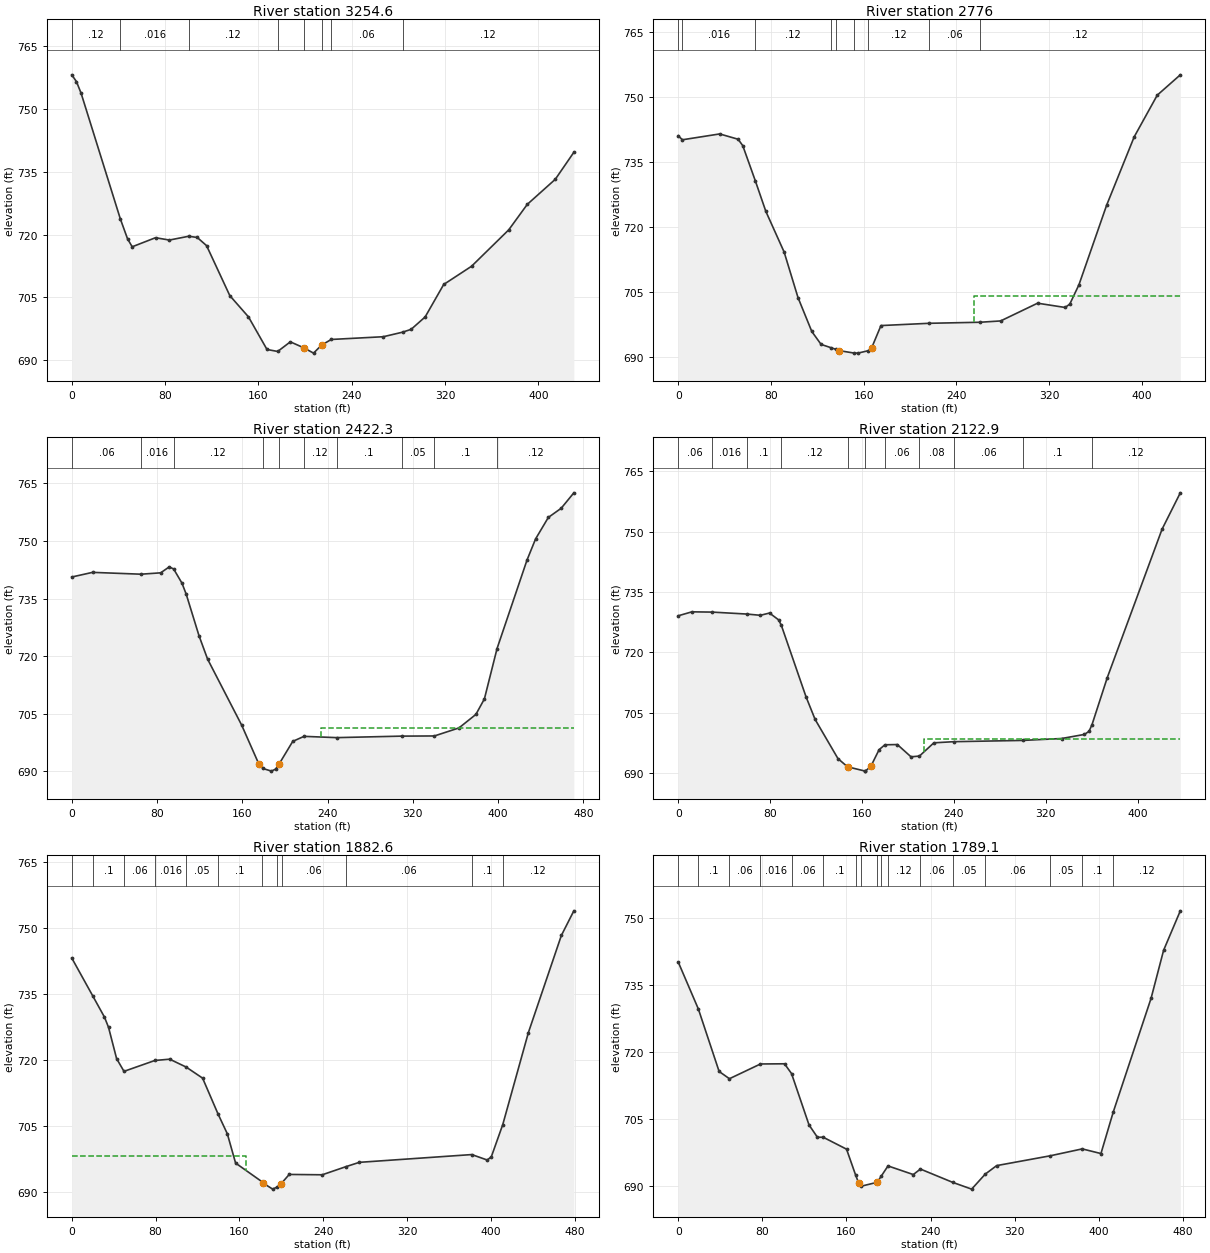
Type RM Length L Ch R = 1 ,3254.6  ,480.4,478.5,476.5
XS GIS Cut Line= 2
     1728682.705      420836.807     1728474.649      421213.706
#Sta/Elev= 30
       0   758.2       4  756.59       8   753.8   41.63723.7714    47.8  719.01
    51.8  717.09    71.8  719.26    83.7   718.7  100.26719.6085   107.6  719.32
   115.6  717.36   135.5  705.42   151.5  700.34   167.4  692.54  176.57692.0682
   187.4  694.37   199.2  692.91   207.3  691.67   214.2  693.59  222.49694.9363
   267.1  695.59   283.6696.6755     291  697.36     303  700.32   318.9  708.08
   342.8  712.44   374.7  721.15   390.6  727.24   414.6  733.23   430.5  739.68
#Mann= 8 ,-1 , 0
       0     .12       0   41.63    .016       0  100.26     .12       0
  176.57     .04       0   199.2    .045       0   214.2     .04       0
  222.49     .06       0   283.6     .12       0
Bank Sta=199.2,214.2
XS Rating Curve= 0 ,0
Exp/Cntr=0.3,0.1

Type RM Length L Ch R = 1 ,2776    ,356.8,353.7,350.4
XS GIS Cut Line= 2
     1728246.928      420633.703     1728076.355       421032.14
#Sta/Elev= 30
       0  741.06    3.56740.1166    35.8  741.47    51.7  740.24    55.7  738.76
    66.5730.6685    75.6  723.59    91.4  714.18   103.4  703.64   115.3  695.81
   123.3  692.83  132.07692.0461   136.3  691.67   139.2  691.37   151.3  690.85
   155.1  690.81   164.2 691.381     167  692.06     175  697.18  216.59697.7042
  260.58697.9473   278.3  698.25   310.2  702.35     334  701.36     338  702.15
   345.9  706.61   369.8     725   393.6   740.8   413.5  750.43   433.4  755.13
#Mann= 9 ,-1 , 0
       0     .05       0    3.56    .016       0    66.5     .12       0
  132.07     .04       0   136.3    .045       0   151.3     .04       0
   164.2     .12       0  216.59     .06       0  260.58     .12       0
#XS Ineff= 2 , 0
                          255.62          703.93
Permanent Ineff=
       F       F
Bank Sta=139.2,167
XS Rating Curve= 0 ,0
Exp/Cntr=0.3,0.1

Type RM Length L Ch R = 1 ,2422.3  ,301.1,299.4,297.7
XS GIS Cut Line= 3
     1727909.682      420455.946     1727909.682      420459.462
     1727788.595      420911.047
#Sta/Elev= 30
       0  740.63    19.5  741.84   64.98741.3624    83.4  741.72    91.4  743.26
   95.56742.7272   103.4  739.02   107.4  736.12   119.4   725.3   127.4  719.25
   159.4  702.03   175.4  691.97   179.3  690.75   187.3  690.06   191.3   690.6
   194.3  691.82   207.3  697.81  217.88699.1177  248.46698.7866  309.61699.1797
  340.19699.2222   363.2  701.31   379.1  704.83   387.1  708.88  398.96 721.993
   427.1  745.07   435.1  750.55   447.1  756.16   459.1  758.53     471  762.56
#Mann= 10 ,-1 , 0
       0     .06       0   64.98    .016       0   95.56     .12       0
   179.3    .045       0   194.3     .04       0  217.88     .12       0
  248.46      .1       0  309.61     .05       0  340.19      .1       0
  398.96     .12       0
#XS Ineff= 2 , 0
                          233.85          701.22
Permanent Ineff=
       F       F
Bank Sta=175.4,194.3
XS Rating Curve= 0 ,0
Exp/Cntr=0.3,0.1

Type RM Length L Ch R = 1 ,2122.9  ,250.2,240.3,230.5
XS GIS Cut Line= 2
     1727603.952      420401.115     1727522.358      420830.613
#Sta/Elev= 30
       0  729.08    11.9  730.06   29.64 729.995    59.7 729.508    71.5   729.2
    79.5  729.76    87.4  728.06   89.76726.7207   111.3  708.91   119.2  703.29
   139.1  693.55   147.4  691.52   162.4  690.47     163  690.44  167.84   691.7
   174.9  695.77  179.95696.9919   190.8  697.05   202.7     694  210.02694.1849
   222.6  697.48  240.08697.7643  300.21698.0792   333.8  698.55   353.7  699.57
   357.7  700.33  360.33702.0198   373.6   713.7   421.3  750.61   437.2  759.66
#Mann= 11 ,-1 , 0
       0     .06       0   29.64    .016       0    59.7      .1       0
   89.76     .12       0   147.4    .045       0   162.4     .04       0
  179.95     .06       0  210.02     .08       0  240.08     .06       0
  300.21      .1       0  360.33     .12       0
#XS Ineff= 2 , 0
                          214.19          698.39
Permanent Ineff=
       F       F
Bank Sta=147.4,167.84
XS Rating Curve= 0 ,0
Exp/Cntr=0.3,0.1

Type RM Length L Ch R = 1 ,1882.6  ,94.6,93.5,92.4
XS GIS Cut Line= 4
     1727315.559      420350.849     1727314.897      420452.135
     1727372.189      420681.301      1727364.97      420822.865
#Sta/Elev= 30
       0  743.21   20.31734.4756    31.2  729.78    35.1  727.45    42.8  720.34
   49.85717.4441   79.38719.9211    93.5  720.21  109.16718.4262   124.9   715.9
   139.6707.7742   148.5  703.25   156.4  696.59   181.3   692.4  182.94691.9991
   191.8  690.67   196.3  691.17   199.7  691.82  200.49692.0732   207.6  694.01
   239.1  693.93  261.37 695.749   274.5  696.76  381.85698.5264   396.6  697.29
   400.5  698.01  411.42705.3242   435.9  726.26   467.4  748.35   479.3  753.94
#Mann= 12 ,-1 , 0
       0     .12       0   20.31      .1       0   49.85     .06       0
   79.38    .016       0  109.16     .05       0   139.6      .1       0
   181.3    .045       0   196.3     .12       0  200.49     .06       0
  261.37     .06       0  381.85      .1       0  411.42     .12       0
#XS Ineff= 2 , 0
          166.43  698.21
Permanent Ineff=
       F       F
Bank Sta=182.94,199.7
XS Rating Curve= 0 ,0
Exp/Cntr=0.3,0.1

Type RM Length L Ch R = 1 ,1789.1  ,258.1,265.5,272.9
XS GIS Cut Line= 4
     1727227.971      420352.004     1727226.355       420476.44
     1727299.272      420719.496     1727298.369      420818.877
#Sta/Elev= 30
       0  740.12   19.16729.6077    38.9  715.64    48.7  714.02   78.23717.3177
   101.1  717.36  107.77 715.175   124.4  703.69   132.4  700.92  137.87700.9318
   160.1  698.26  168.71692.4865  171.73  690.62   174.3  689.99   189.3  690.85
  193.15692.2402  199.55694.5119   223.6  692.58  230.38693.8092  261.22690.8197
   279.1  689.32  292.05692.6796   302.9  694.58  353.72696.7709  384.29698.3204
   402.1  697.28  413.83706.5847   449.8  732.02   461.7  742.75   477.6  751.58
#Mann= 17 ,-1 , 0
       0     .12       0   19.16      .1       0    48.7     .06       0
   78.23    .016       0  107.77     .06       0  137.87      .1       0
  168.71     .12       0   174.3    .045       0   189.3     .12       0
  193.15      .1       0  199.55     .12       0  230.38     .06       0
  261.22     .05       0  292.05     .06       0  353.72     .05       0
  384.29      .1       0  413.83     .12       0
Bank Sta=171.73,189.3
XS Rating Curve= 0 ,0
Exp/Cntr=0.3,0.1

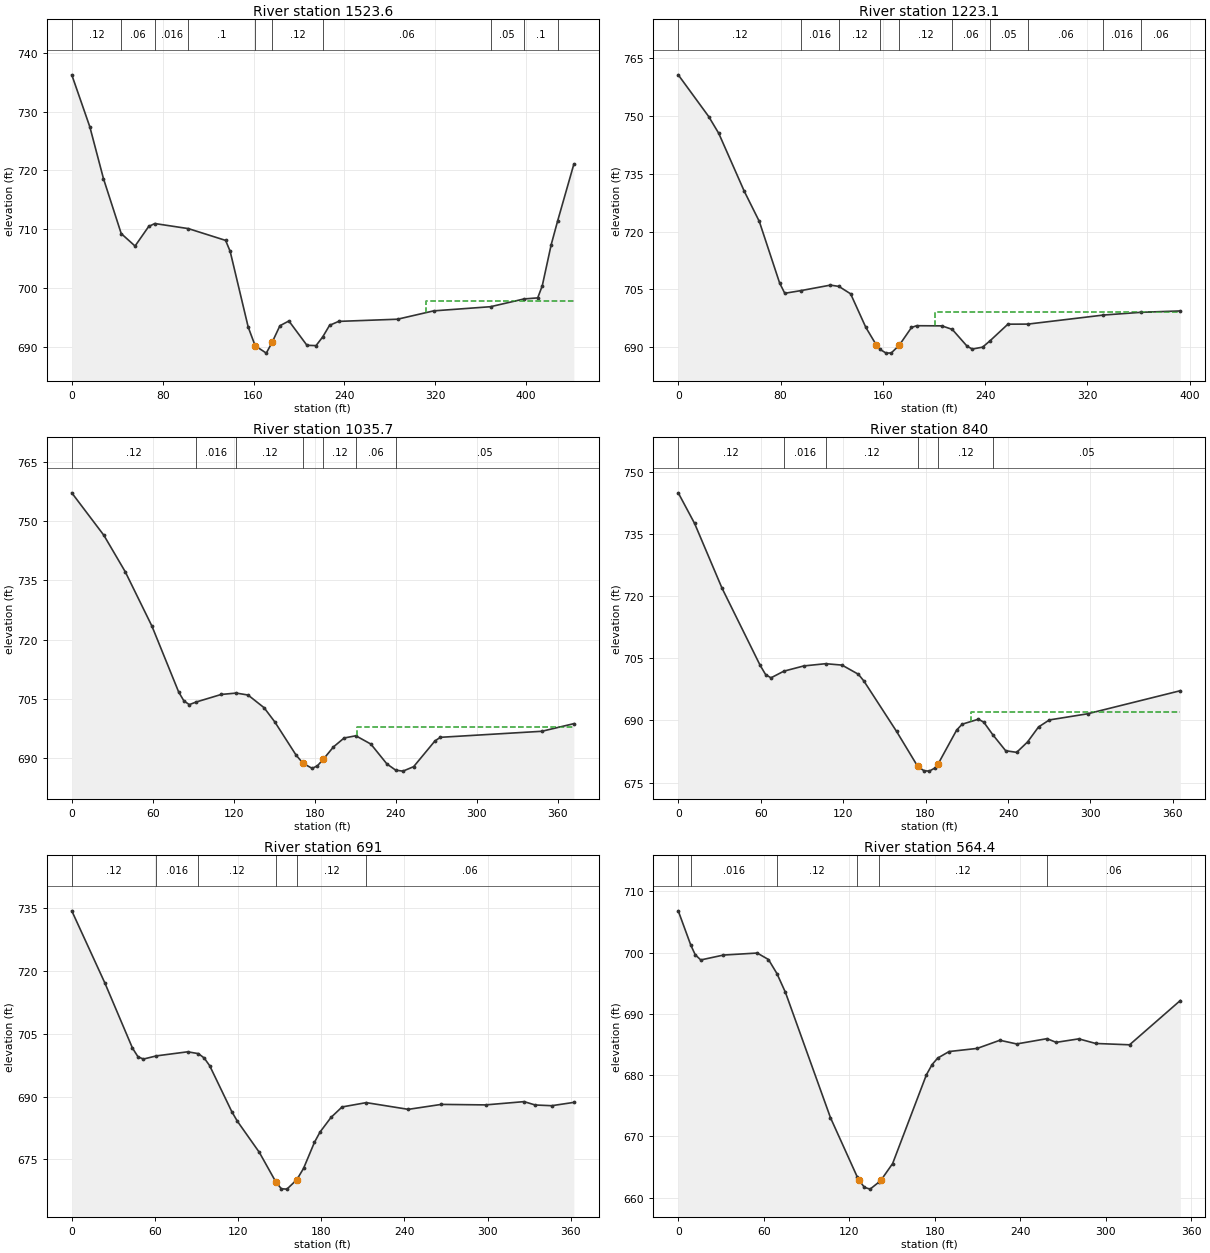
Type RM Length L Ch R = 1 ,1523.6  ,302,300.5,298.9
XS GIS Cut Line= 2
     1726983.184      420357.185     1726970.189      420798.933
#Sta/Elev= 30
       0  736.25    15.9   727.4    27.9  718.59   43.53709.2345    55.7  707.12
    67.7  710.45   73.08710.9489  102.63710.0848   135.4  708.08   139.4  706.22
   155.3  693.32   161.4  690.16   171.2   688.9   176.4  690.76   183.2  693.56
   191.1  694.37     207  690.23     215  690.18  220.82691.6452   226.9  693.63
   234.9   694.3   286.7  694.67   318.5  696.09  368.56696.7974  398.11698.1196
   410.1   698.3   414.1  700.35     422  707.38  427.66711.4084   441.9  721.05
#Mann= 10 ,-1 , 0
       0     .12       0   43.53     .06       0   73.08    .016       0
  102.63      .1       0   161.4    .045       0   176.4     .12       0
  220.82     .06       0  368.56     .05       0  398.11      .1       0
  427.66     .12       0
#XS Ineff= 2 , 0
                           311.8          697.76
Permanent Ineff=
       F       F
Bank Sta=161.4,176.4
XS Rating Curve= 0 ,0
Exp/Cntr=0.3,0.1

Type RM Length L Ch R = 1 ,1223.1  ,185.9,187.4,188.8
XS GIS Cut Line= 2
     1726671.758      420363.776     1726687.033      420756.099
#Sta/Elev= 30
       0  760.67    23.8  749.86    31.7  745.48    51.6   730.5    63.4  722.64
    79.3  706.66    83.3  704.01   96.07704.7118     119  706.13  125.62705.7944
   134.8  703.87   146.7  695.16   154.7  690.71   157.8  689.45   162.6  688.49
   166.6  688.54   172.8  690.53   182.4  695.14   186.4   695.6   206.2  695.56
   214.3694.6384     226  690.24     230  689.55     238  690.04  243.85 691.702
   257.8     696  273.41696.0176  332.53698.3652  362.08699.0795   392.6  699.43
#Mann= 10 ,-1 , 0
       0     .12       0   96.07    .016       0  125.62     .12       0
   157.8    .045       0   172.8     .12       0   214.3     .06       0
  243.85     .05       0  273.41     .06       0  332.53    .016       0
  362.08     .06       0
#XS Ineff= 2 , 0
                          201.12          699.17
Permanent Ineff=
       F       F
Bank Sta=154.7,172.8
XS Rating Curve= 0 ,0
Exp/Cntr=0.3,0.1

Type RM Length L Ch R = 1 ,1035.7  ,190.8,195.7,200.5
XS GIS Cut Line= 2
     1726496.634      420367.482     1726487.748      420739.392
#Sta/Elev= 30
       0   757.2    23.8  746.43    39.6  737.21    59.4  723.41    79.2  706.72
    83.1  704.45    87.1  703.52   92.32704.1945   110.8   706.1  121.86706.4432
   130.6  705.95   142.5  702.73   150.4  699.15   166.2  690.72   171.4  688.64
   178.1  687.36     182  688.01   186.4  689.68   193.9   692.8   201.8  695.06
  210.49695.6186   221.6  693.52   233.5  688.48  240.03686.9011   245.4  686.66
   253.3  687.79   269.1  694.32   273.1  695.23   348.3  696.76     372  698.69
#Mann= 7 ,-1 , 0
       0     .12       0   92.32    .016       0  121.86     .12       0
   171.4    .045       0   186.4     .12       0  210.49     .06       0
  240.03     .05       0
#XS Ineff= 2 , 0
                          211.24          697.96
Permanent Ineff=
       F       F
Bank Sta=171.4,186.4
XS Rating Curve= 0 ,0
Exp/Cntr=0.3,0.1

Type RM Length L Ch R = 1 ,840     ,149.3,149,148.5
XS GIS Cut Line= 2
      1726341.12      420355.538     1726254.779      420710.639
#Sta/Elev= 30
       0  744.92    11.9  737.54    31.8  721.97    59.6  703.31    63.6  701.07
    67.5  700.29   76.88701.8953    91.4  703.16  107.27703.6972   119.2  703.36
   131.1  701.15   135.1  699.53   158.9  687.36   174.2  678.97   178.8  677.88
   182.7  677.78   186.7  678.51   189.2  679.55   202.6  687.67   206.6   689.1
   218.5  690.31   222.4  689.58  228.85 686.596   238.3   682.7   246.3  682.31
   254.2  684.81   262.2  688.43   270.1  690.13   297.9  691.61   365.4  697.18
#Mann= 6 ,-1 , 0
       0     .12       0   76.88    .016       0  107.27     .12       0
   174.2    .045       0   189.2     .12       0  228.85     .05       0
#XS Ineff= 2 , 0
                          212.92          691.94
Permanent Ineff=
       F       F
Bank Sta=174.2,189.2
XS Rating Curve= 0 ,0
Exp/Cntr=0.3,0.1

Type RM Length L Ch R = 1 ,691     ,126.9,126.6,126.4
XS GIS Cut Line= 2
     1726188.853      420341.079     1726109.654      420694.462
#Sta/Elev= 30
       0  734.28    23.9  717.06    43.8  701.55    47.8  699.47    51.7  698.94
    61.1699.6995    83.6  700.67   91.37700.2333    95.5   699.2    99.5  697.35
   115.4  686.43   119.4  684.15   135.3   676.7   147.3   669.6   151.2  668.01
   155.2  667.93   162.3  670.16   167.2  672.87   175.1  679.11   179.1  681.54
     187  685.02     195  687.52  212.44 688.553   242.8  686.95   266.6  688.13
   298.5  688.01   326.3  688.79   334.3  687.99   346.2  687.82   362.2  688.61
#Mann= 6 ,-1 , 0
       0     .12       0    61.1    .016       0   91.37     .12       0
   147.3    .045       0   162.3     .12       0  212.44     .06       0
Bank Sta=147.3,162.3
XS Rating Curve= 0 ,0
Exp/Cntr=0.3,0.1

Type RM Length L Ch R = 1 ,564.4   ,127.5,125.4,123.2
XS GIS Cut Line= 2
     1726059.499      420333.008     1725986.138      420677.484
#Sta/Elev= 30
       0  706.81    8.82701.2054    11.9  699.65    15.8  698.79    31.7  699.59
    55.4  699.92    63.3  698.86   69.21696.5789    75.2   693.5   106.8  673.04
   125.7  663.31   126.6  662.92   130.6  661.67   134.6  661.38   140.7  662.51
   142.5  662.93   150.4  665.56   174.1  680.05   178.1  681.72     182  682.77
     190  683.84   209.7  684.35   225.6  685.68   237.4  685.08  258.67685.9402
   265.1  685.34     281  685.91   292.8  685.16   316.6  684.94   352.2  692.17
#Mann= 6 ,-1 , 0
       0     .12       0    8.82    .016       0   69.21     .12       0
   125.7    .045       0   140.7     .12       0  258.67     .06       0
Bank Sta=126.6,142.5
XS Rating Curve= 0 ,0
Exp/Cntr=0.3,0.1

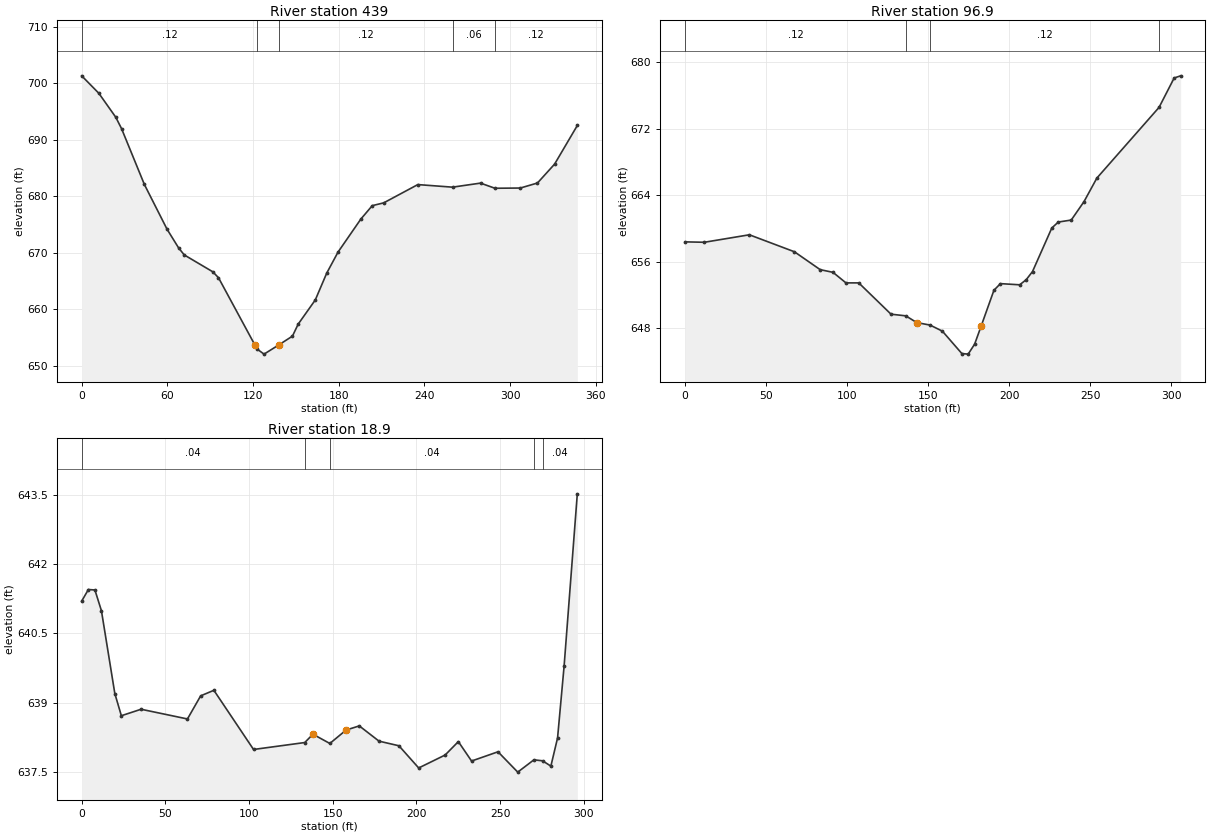
Type RM Length L Ch R = 1 ,439     ,342,342.1,342
XS GIS Cut Line= 2
     1725922.981      420319.946     1725883.073      420664.764
#Sta/Elev= 30
       0  701.35      12  698.26    23.9     694    27.9     692    43.9   682.1
    59.8  674.16    67.8  670.89    71.8  669.62    91.8  666.63    95.8  665.58
  121.42   653.6   123.1  652.89   127.7  652.04   138.1  653.68   147.6  655.23
   151.6  657.35   163.6  661.64   171.6  666.39   179.5  670.11   195.5  675.97
   203.5  678.35   211.5  678.84   235.4  682.08  259.69681.6234   279.3  682.34
  289.42681.4293   307.2  681.47   319.2  682.36   331.2  685.71   347.1  692.55
#Mann= 5 ,-1 , 0
       0     .12       0   123.1    .045       0   138.1     .12       0
  259.69     .06       0  289.42     .12       0
Bank Sta=121.42,138.1
XS Rating Curve= 0 ,0
Exp/Cntr=0.3,0.1

Type RM Length L Ch R = 1 ,96.9    ,78,78,78
XS GIS Cut Line= 2
      1725583.49      420287.392     1725548.078      420591.096
#Sta/Elev= 30
       0  658.38    11.9  658.33    39.7  659.23    67.5  657.19    83.4  655.04
    91.3  654.72    99.3  653.45   107.2  653.45   127.1  649.69   136.2  649.49
     143  648.68   151.2  648.38   158.8  647.65   170.8  644.96   174.7  644.89
   178.7  646.09   182.7  648.25   190.6  652.56   194.6  653.36   206.5  653.22
   210.5  653.83   214.4  654.81   226.3  660.04   230.3  660.76   238.3     661
   246.2  663.22   254.1  666.04  292.49674.5404   301.8  678.07   305.8  678.33
#Mann= 4 ,-1 , 0
       0     .12       0   136.2    .045       0   151.2     .12       0
  292.49     .06       0
Bank Sta=143,182.7
XS Rating Curve= 0 ,0
Exp/Cntr=0.3,0.1

Type RM Length L Ch R = 1 ,18.9    ,18.4,18.9,19.5
XS GIS Cut Line= 2
     1725505.886      420279.951     1725471.583      420574.151
#Sta/Elev= 30
       0   641.2       4  641.45     7.9  641.44    11.8  640.99    19.8   639.2
    23.7  638.72    35.5  638.86    63.2  638.65    71.1  639.15      79  639.27
   102.7  637.99   133.3  638.14   138.2  638.32   148.3  638.12     158  638.41
   165.9   638.5   177.7  638.17   189.6  638.07   201.4  637.59   217.2  637.87
   225.1  638.16     233  637.74   248.8  637.94   260.6   637.5  270.25637.7658
  275.43 637.745   280.4  637.63   284.4  638.24   288.3  639.79   296.2  643.52
#Mann= 5 ,-1 , 0
       0     .04       0   133.3    .045       0   148.3     .04       0
  270.25     .12       0  275.43     .04       0
Bank Sta=138.2,158
XS Rating Curve= 0 ,0
Exp/Cntr=0.3,0.1

Chan Stop Cuts=-1
Use User Specified Reach Order=0
Composite Channel Slope=5